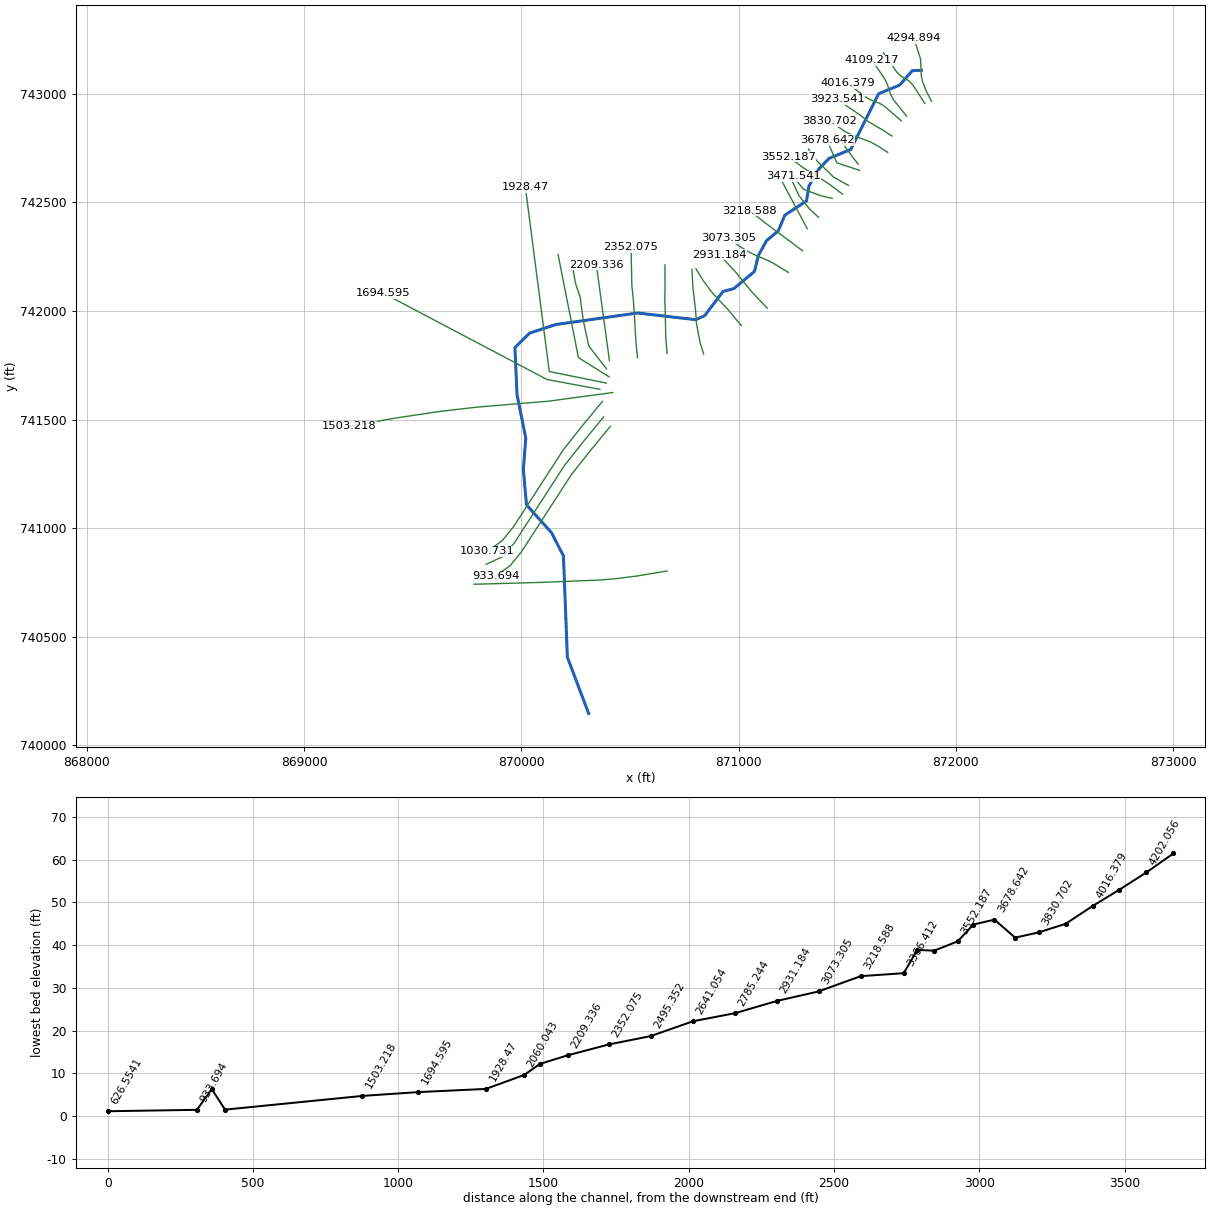
--- 8701_ras.prj (project) ---

Proj Title=8701
Current Plan=p01
Default Exp/Contr=0.3,0.1
English Units
Geom File=g01
Flow File=f01
Plan File=p01
Y Axis Title=Elevation
X Axis Title(PF)=Main Channel Distance
X Axis Title(XS)=Station
BEGIN DESCRIPTION:
RFD model 8701 exported to HEC-RAS
END DESCRIPTION:

--- 8701_ras.p01 (plan) ---

Plan Title=Plan 01
Program Version=4.10
Short Identifier=Plan 01
Geom File=g01
Flow File=f01
Subcritical Flow
Calc Critical at every XS
Secant Critical Depth

--- 8701_ras.f01 (steady flow) ---

Flow Title=Flow 01
Program Version=5.01
Number of Profiles= 6
Profile Names=10yr,25yr,50yr,100yr,100plus,500yr
River Rch & RM=8701,30,4294.894
  148.08  236.51  318.85  393.98  575.21  1017.3
River Rch & RM=8701,30,3073.305
  155.99   249.2  336.04  415.27  606.29 1064.56
River Rch & RM=8701,30,2931.184
  162.99  260.44  351.27  434.13  633.83 1106.16
River Rch & RM=8701,30,2785.244
  165.44  264.39  356.61  440.75  643.49  1120.7
River Rch & RM=8701,30,2641.054
  170.74  272.89  368.13  455.02  664.33 1151.94
River Rch & RM=8701,30,2495.352
  174.38  278.74  376.06  464.85  678.68 1173.37
River Rch & RM=8701,30,2352.075
  193.97  310.22  418.71  517.68  755.82 1287.52
River Rch & RM=8701,30,2209.336
  198.72  317.85  429.05  530.48   774.5 1314.87
River Rch & RM=8701,30,2115.303
   200.7  321.02  433.34  535.79  782.25 1326.19
River Rch & RM=8701,30,2060.043
  201.49  322.29  435.05  537.91  785.35 1330.71
River Rch & RM=8701,30, 1928.47
  901.28 1442.73 1951.08 2410.69 3519.61 4809.05
River Rch & RM=8701,30,1694.595
  904.98 1448.73 1959.27 2420.88 3534.48 4826.77
River Rch & RM=8701,30,1503.218
  906.69  1451.5 1963.05 2425.57 3541.34 4834.93
River Rch & RM=8701,30,1030.731
 1409.43 2260.31  3061.6 3785.66 5527.07 7093.81
River Rch & RM=8701,30,626.5541
 1450.57 2327.44 3153.63 3900.52 5694.76 7282.47
Boundary for River Rch & Prof#=8701,30,1
Up Type= 0
Dn Type= 2
Boundary for River Rch & Prof#=8701,30,2
Up Type= 0
Dn Type= 2
Boundary for River Rch & Prof#=8701,30,2
Up Type= 0
Dn Type= 2
Boundary for River Rch & Prof#=8701,30,2
Up Type= 0
Dn Type= 2
Boundary for River Rch & Prof#=8701,30,2
Up Type= 0
Dn Type= 2
Boundary for River Rch & Prof#=8701,30,2
Up Type= 0
Dn Type= 2

--- 8701_ras.g01 (geometry) ---

Geom Title=8701
Program Version=4.10

River Reach=8701,30
Reach XY= 30
871842.236872632743107.477331559 871799.87576152743106.088442678
871741.542428185743039.421775989871645.014650401742999.838442644
871516.112795419742742.863439918871416.449094396742701.815977978
871370.177938528742653.454428108871324.010802201742574.324059275
871312.889167279742506.594213409871212.985255363 742440.47173731
871182.850906497742368.164664447871128.848813395742323.346144867
871090.927551305742254.508710592871073.557257322742181.681914963
870978.347983737742102.616220475870928.955486883742089.767370944
870843.910411113741978.023838289870802.884750443741959.535790282
870535.519471967741990.429172217870158.903539292  741937.3384427
870038.312739247741897.799030952869970.577533057741831.123479231
869980.254905779741614.695950562870020.552663568741414.623396614
870009.486518063741268.532390186870023.854917114741106.959800829
870139.356736634740978.712502233 870194.04423668740871.941669022
870211.916034289740406.528688232870309.797670144740147.296254263

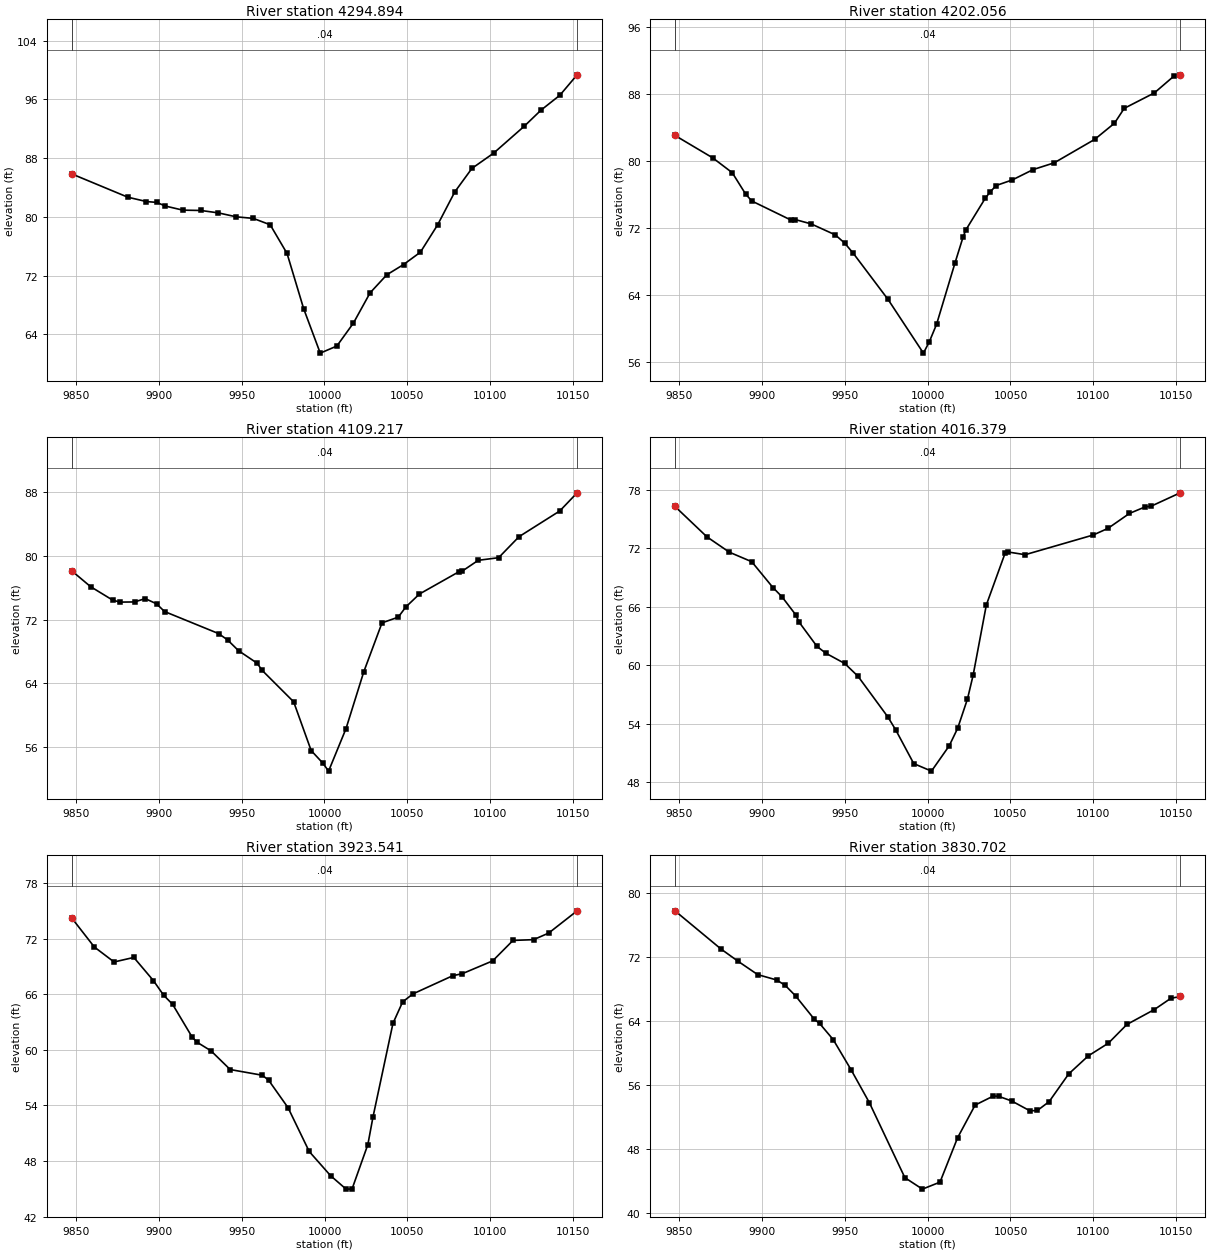
Type RM Length L Ch R = 1 ,4294.894,92.838300,92.838300,92.838300
XS GIS Cut Line= 6
871888.394620975742965.012629377871862.887511225743014.699440774
871846.163532543743058.064407126871841.032422065743085.786206503
871837.584425323743161.230832711871807.395956156743254.772556433
#Sta/Elev= 28
9847.70285.84384 9881.4182.679259892.65182.085899898.92881.969499903.87681.48227
9914.594 80.91619925.47480.87079 9936.0380.541199946.74780.007429957.08579.79148
9967.255 78.92179977.42575.012019987.43867.486289997.43961.4327210007.4562.39921
10017.4565.5294410027.4969.6457810037.5872.1073710047.6673.5015510057.8475.18779
 10068.278.9031110078.5683.3981410088.9186.6059110101.9688.6777910120.5792.37278
10130.5894.5471610141.9196.5666610152.3499.35402
#Mann= 3 , 0 , 0
9847.702    0.04       09847.702    0.04       010152.34    0.04       0
#XS Ineff= 2 , 0
       0                               0
Bank Sta=9847.702,10152.34
Exp/Cntr=0.3,0.1

Type RM Length L Ch R = 1 ,4202.056,92.838300,92.838300,92.838300
XS GIS Cut Line= 6
 871857.52314137742955.661717225871801.649947582743041.370681984
871783.093847999743059.746857364871748.519370237743080.698628992
871730.156067762 743097.33330928871666.426267828743188.054493711
#Sta/Elev= 30
9847.68683.061769870.45680.377819882.23178.601669890.34776.028749894.00675.21548
9917.55572.940549920.133 72.99529929.79872.474369944.36871.158789950.05670.16732
9955.21368.955549976.17163.432679997.50257.00331   1000158.3305510005.4460.45072
10016.6167.8347410021.3670.8563910023.0171.7202510034.85 75.554810037.9176.32983
10041.39 77.065710051.0877.7335110063.7378.9783110076.3779.7809710100.7582.58293
10112.7384.52428 10118.686.3034310136.76 88.149710148.6790.1816510152.3390.31625
#Mann= 3 , 0 , 0
9847.686    0.04       09847.686    0.04       010152.33    0.04       0
#XS Ineff= 2 , 0
       0                               0
Bank Sta=9847.686,10152.33
Exp/Cntr=0.3,0.1

Type RM Length L Ch R = 1 ,4109.217,92.838300,92.838300,92.838300
XS GIS Cut Line= 6
871773.975806182742896.485198951871712.882867134742972.291680814
871699.707411783742997.838195065871685.328723767743041.583064796
871673.066216978743068.045387769871615.118655283 743153.51581696
#Sta/Elev= 30
9847.65678.117599858.93776.146189872.18674.463289876.58574.207049885.43474.22907
 9891.83 74.64859898.683 73.99589903.51573.023429936.09270.254149941.50569.46276
9948.15468.102619959.40566.523189962.30465.647939981.40361.674889991.94955.55312
    999953.9700510002.4652.9652510012.9858.3094310023.6765.4363410034.6971.60038
10044.4772.3143610049.07 73.598610057.2775.2243810080.8677.9979810083.1478.11262
10092.7479.4600810105.0379.7899810117.3382.4286210141.9185.6633910152.38 87.9421
#Mann= 3 , 0 , 0
9847.656    0.04       09847.656    0.04       010152.38    0.04       0
#XS Ineff= 2 , 0
       0                               0
Bank Sta=9847.656,10152.38
Exp/Cntr=0.3,0.1

Type RM Length L Ch R = 1 ,4016.379,92.838300,92.838300,92.838300
XS GIS Cut Line= 6
871749.274972271 742875.21598337 871671.89175287742942.150305888
871649.456896729742955.555336212871610.197491487742970.562464734
871583.040003668742985.261583008871501.440349498743048.479559323
#Sta/Elev= 30
9847.64376.302179866.93373.178679880.44671.60276 9893.9670.624399906.794 67.9622
9912.19267.025399920.502 65.16829922.43364.439769933.272 61.93489938.51361.24027
9950.01160.176389958.039 58.86239976.14654.660239980.93353.309239991.67349.88835
10002.3649.1154410013.0551.7106410018.1853.5239710024.0956.53303 10027.558.97435
10035.4666.1859310046.8371.5320110048.5171.6254510058.8871.3457810099.8973.36756
10108.7874.0461110121.7775.5837710131.2476.2570310134.7576.3201410152.3677.70063
#Mann= 3 , 0 , 0
9847.643    0.04       09847.643    0.04       010152.36    0.04       0
#XS Ineff= 2 , 0
       0                               0
Bank Sta=9847.643,10152.36
Exp/Cntr=0.3,0.1

Type RM Length L Ch R = 1 ,3923.541,92.838300,92.838300,92.838300
XS GIS Cut Line= 6
871706.369744422742805.327468533871667.327723179742830.524828339
871596.456846034742871.886574072871557.593321692742903.331126112
871491.792961673742947.334907633871453.797358636742975.155931093
#Sta/Elev= 30
9847.624 74.18819861.15671.081529873.05869.46805 9884.9669.958569896.78767.45704
 9902.9765.877899908.36564.897219919.94461.423469922.80960.839929931.52259.88103
9943.10157.860179962.48757.244689966.25856.716289978.00953.741769990.77549.01719
10003.6946.4010710012.96 44.965410016.5944.9552710026.1549.7637510029.2752.76015
 10041.362.8482110047.1465.1618210053.3366.0219910077.3967.9874510083.11 68.2031
10101.4569.5867910113.7271.7946910126.1271.8774610135.2172.58481 10152.474.98861
#Mann= 3 , 0 , 0
9847.624    0.04       09847.624    0.04       0 10152.4    0.04       0
#XS Ineff= 2 , 0
       0                               0
Bank Sta=9847.624,10152.4
Exp/Cntr=0.3,0.1

Type RM Length L Ch R = 1 ,3830.702,80.689600,80.689600,80.689600
XS GIS Cut Line= 6
871686.772554411742729.735515002871646.703887531742756.073400426
871607.235782206742777.787301126871522.408902297742810.093684935
871490.986030991742825.038855195 871420.50431355742874.412212041
#Sta/Elev= 30
9847.61377.711289875.40372.938469885.63571.418089897.50869.747099908.92169.07577
9914.08268.411389920.33567.097849931.74864.157119934.82863.652749943.04961.63657
9953.955 57.82529964.86153.763269986.30744.386769996.89342.95413 10007.5  43.828
 10018.149.3673610028.6953.4516110039.6454.5767610042.8654.5446910050.7253.96681
10061.7952.7282510066.2452.7769210073.3253.8777910085.1457.3421710096.9759.59854
10109.0761.1814410120.2563.5203310136.7965.3794910146.7266.7798710152.3767.01561
#Mann= 3 , 0 , 0
9847.613    0.04       09847.613    0.04       010152.37    0.04       0
#XS Ineff= 2 , 0
       0                               0
Bank Sta=9847.613,10152.37
Exp/Cntr=0.3,0.1

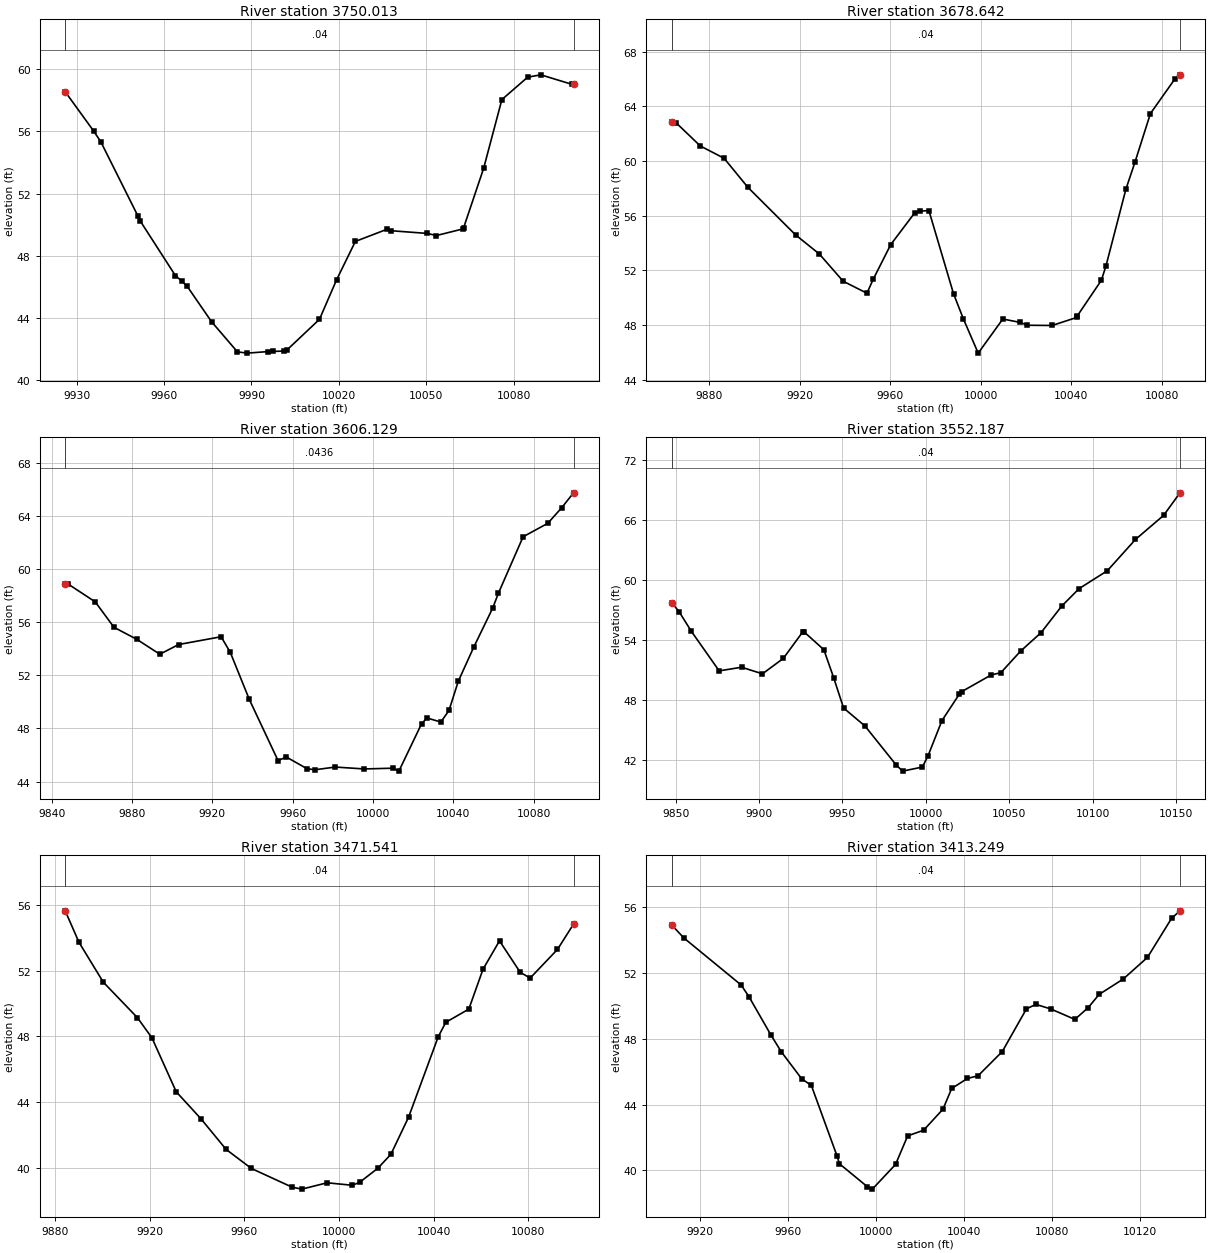
Type RM Length L Ch R = 1 ,3750.013,71.370800,71.370800,71.370800
XS GIS Cut Line= 6
871551.078745323742675.448104247871526.099227609742706.704230979
871508.970183792 742730.68428853871507.649511712742732.186228746
871469.561087376742785.151649122871444.564125542742813.417358667
#Sta/Elev= 30
9926.07858.558389935.81456.035439938.30555.333099951.10650.531759951.83250.23855
9963.90846.720439966.08946.37025 9967.9846.023779976.284 43.75989985.18541.81397
9988.57341.733429995.55941.831359997.55941.8461310001.0241.86392 10002.141.92074
10013.3443.9100810019.2246.4587710025.6648.9240110036.3549.6950810037.9849.61147
10050.2949.4392710053.4849.3026710062.6149.73103 10062.849.7990910069.6853.62887
10075.9458.0550810084.7859.4949610089.2959.6473110099.8759.0432510100.5359.05642
#Mann= 3 , 0 , 0
9926.078    0.04       09926.078    0.04       010100.53    0.04       0
#XS Ineff= 2 , 0
       0                               0
Bank Sta=9926.078,10100.53
Exp/Cntr=0.3,0.1

Type RM Length L Ch R = 1 ,3678.642,72.512500,72.512500,72.512500
XS GIS Cut Line= 4
871557.018855041742647.092064623871452.558050745742681.528013315
871419.943035643742756.904495996871407.293289735742787.056409977
#Sta/Elev= 30
 9863.3162.862259865.43662.779279875.96561.109469886.49560.208589897.02458.08018
9918.083 54.60459928.61253.202739939.14251.209719949.67150.33243 9952.4551.35332
  9960.253.89249 9970.73 56.19839973.30156.343459977.08456.37849 9987.9850.28728
9992.33348.451469998.87645.9470510009.7748.4448710017.5148.1921310020.6747.98662
10031.5647.9705710042.4648.55814 10042.748.6689410053.36 51.278910055.4352.35406
10064.2157.9497810068.2159.9204810075.0563.48323 10085.966.0196710088.1366.31621
#Mann= 3 , 0 , 0
 9863.31    0.04       0 9863.31    0.04       010088.13    0.04       0
#XS Ineff= 2 , 0
       09976.416                       0
Bank Sta=9863.31,10088.13
Exp/Cntr=0.3,0.1

Type RM Length L Ch R = 1 ,3606.129,53.942000,53.942000,53.942000
XS GIS Cut Line= 4
871506.278791956742577.789874253871438.253678638742615.182352244
 871360.06670468742691.717524964871321.581503219742745.412744946
#Sta/Elev= 30
9846.72458.891959848.18358.876359861.69257.532399871.00655.617879882.45154.70631
9893.82853.590079903.21154.322379924.34954.907179928.90253.735899938.38450.18822
9952.67945.584389956.88945.844949966.97544.980189970.88244.88665 9981.2745.09282
9995.56644.9502410009.8645.0068110012.8644.7861110024.1648.3538210026.8648.78841
10033.7648.48332 10037.8  49.35410042.46 51.5653 10050.154.1104310059.6257.08177
10062.4158.1841510074.7162.4371610087.0163.4513110093.9564.6287410099.8265.74733
#Mann= 3 , 0 , 0
9846.724  0.0436       09846.724  0.0436       010099.82  0.0436       0
#XS Ineff= 2 , 0
       09928.353                       0
Bank Sta=9846.724,10099.82
Exp/Cntr=0.3,0.1

Type RM Length L Ch R = 1 ,3552.187,80.646100,80.646100,80.646100
XS GIS Cut Line= 6
871478.538713762742537.912216687871414.844546835742585.678590472
871354.074051174742623.868014923871352.346567059 742624.87588328
871302.792566961 742655.73716842871227.838072066742710.806987205
#Sta/Elev= 30
9847.61157.750429852.03456.846389859.42554.869439876.09250.908899889.53351.27416
9902.03350.612689914.53252.154089926.09554.792699927.22654.779699938.853 53.0325
9944.74550.221649950.66447.190739963.53945.378789982.33341.455519986.09640.86213
9997.90641.2706910001.23 42.362810009.6545.9206110020.1548.5933910021.4448.82352
10039.0750.49016   10045 50.730710056.78 52.883110069.0554.7332610081.4657.39701
10091.9159.15383 10108.860.9405510125.6964.0789710142.5866.4930210152.3968.75196
#Mann= 3 , 0 , 0
9847.611    0.04       09847.611    0.04       010152.39    0.04       0
#XS Ineff= 2 , 0
       0 9933.16                       0
Bank Sta=9847.611,10152.39
Exp/Cntr=0.3,0.1

Type RM Length L Ch R = 1 ,3471.541,58.292500,58.292500,58.292500
XS GIS Cut Line= 4
871430.657695959 742518.00808433871378.443866857742530.303163122
871299.756325814742559.575369611871250.684727677 742619.14261227
#Sta/Elev= 26
9884.35655.665029890.16853.746669900.44251.31323 9914.86 49.14679920.98947.91791
9931.26244.626129941.67242.984179952.34141.109349963.01139.94766 9980.1538.81023
 9984.3538.68651 9995.0239.0732610005.6938.9208610008.8339.1095810016.3639.94997
10021.9540.8064910029.43 43.074410041.9447.9759710045.1648.8646210054.8949.66913
10060.8952.1042810067.8553.8325610076.6251.9096510080.8151.5646410092.3453.30903
10099.1354.85458
#Mann= 3 , 0 , 0
9884.356    0.04       09884.356    0.04       010099.13    0.04       0
#XS Ineff= 2 , 0
       0                               0
Bank Sta=9884.356,10099.13
Exp/Cntr=0.3,0.1

Type RM Length L Ch R = 1 ,3413.249,46.837300,46.837300,46.837300
XS GIS Cut Line= 4
871368.212840456742431.150627152 871326.47654582742469.737630361
871278.060813558742530.619973544871237.478961481742618.441545448
#Sta/Elev= 30
9906.99854.924039912.66954.122259938.61251.27594 9942.1350.573039952.23148.22051
 9956.8647.217859966.21145.562629970.56345.168999982.27840.868039983.33940.40222
9996.11638.998869998.34438.8571310008.8940.3578710014.4142.0961210021.6742.44023
10030.4843.7216510034.4544.9807610041.6345.5900810046.4545.7512510057.4747.22514
10068.4849.8232710072.7650.09555 10079.549.8205310090.5149.18218 10096.6    49.9
10101.5350.6995710112.5551.6392610123.5652.9541210134.5855.3390410138.3755.78683
#Mann= 3 , 0 , 0
9906.998    0.04       09906.998    0.04       010138.37    0.04       0
#XS Ineff= 2 , 0
       0                               0
Bank Sta=9906.998,10138.37
Exp/Cntr=0.3,0.1

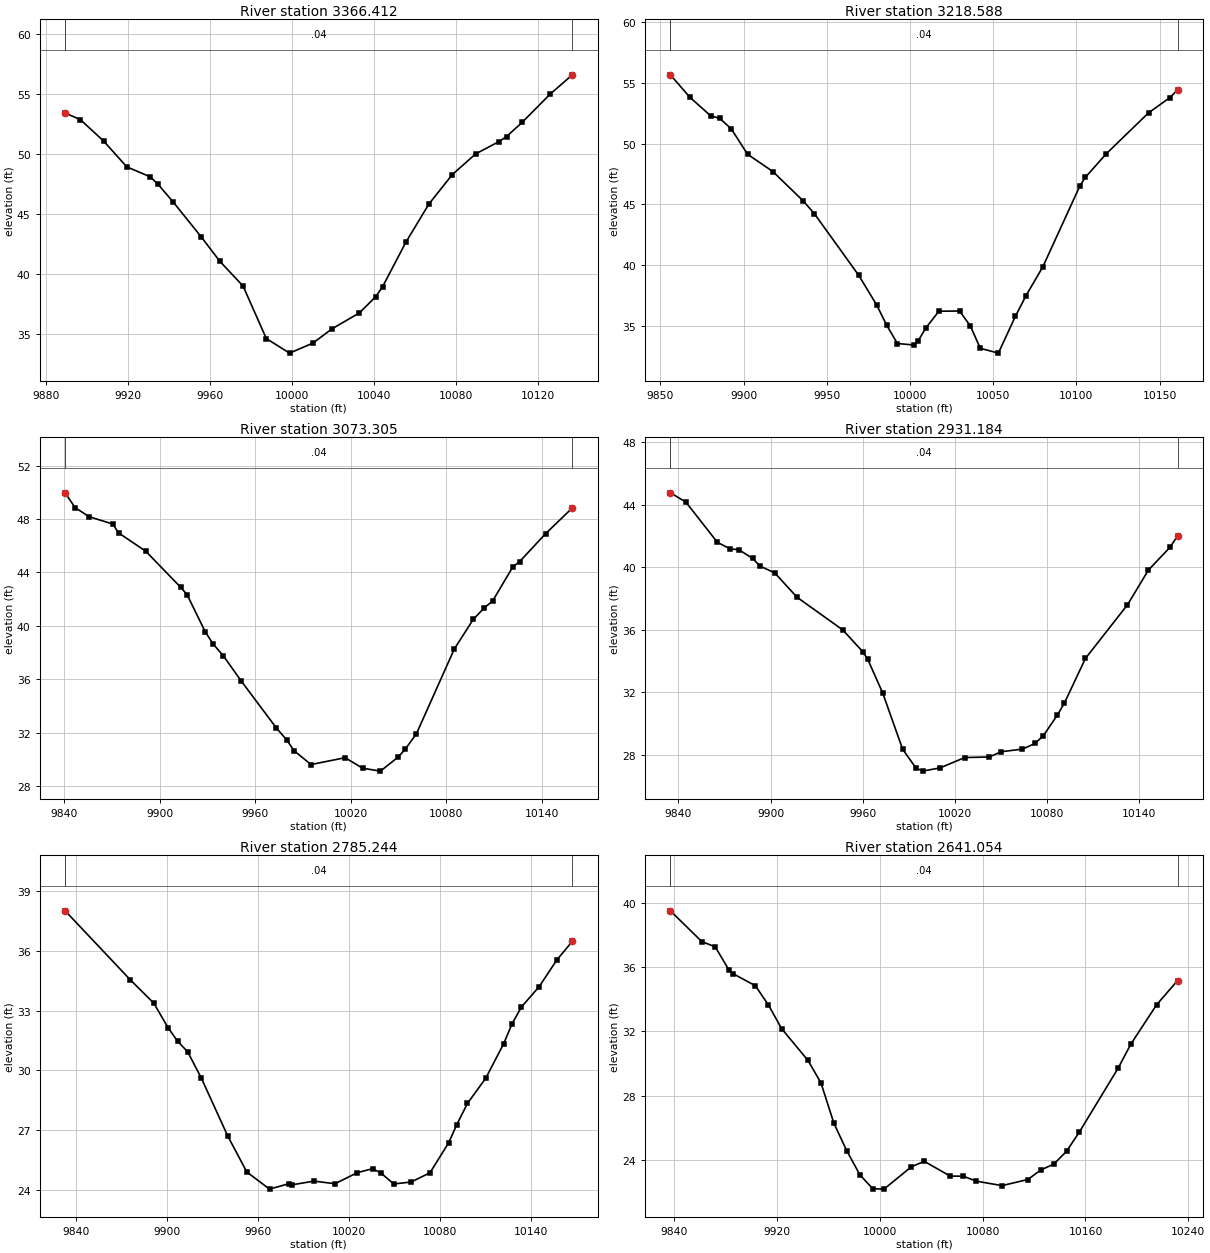
Type RM Length L Ch R = 1 ,3366.412,147.823800,147.823800,147.823800
XS GIS Cut Line= 2
871316.218782297742378.461853124871199.909438301742596.653022628
#Sta/Elev= 26
9889.385 53.39539896.79452.842759908.12751.063349919.45948.909019930.79148.09103
9934.49347.496249942.12345.973069955.75243.079449964.787  41.0589976.11938.99583
9987.45134.627479998.78333.4145410010.1234.2446410019.5335.4419510032.7836.75774
10040.7938.1104110044.1138.9390510055.4442.6293710066.7845.8364610078.1148.26827
10089.4449.9838110100.7751.0063610104.56 51.4348 10112.152.6037710125.8254.96684
10136.6456.57008
#Mann= 3 , 0 , 0
9889.385    0.04       09889.385    0.04       010136.64    0.04       0
#XS Ineff= 2 , 0
       0                               0
Bank Sta=9889.385,10136.64
Exp/Cntr=0.3,0.1

Type RM Length L Ch R = 1 ,3218.588,145.282700,145.282700,145.282700
XS GIS Cut Line= 5
871294.334437921742277.238390081871173.000688144 742367.82844612
 871171.37255597742368.989990619871128.028868987742401.095641229
871051.257587451742461.164822058
#Sta/Elev= 30
 9855.9755.676049867.61953.833119880.09952.303799885.65952.078069892.57951.21802
9902.37449.123849917.53847.704119935.80445.276939942.49844.228329969.23439.12923
9979.93736.701029985.94935.029239992.41733.5202310002.6633.39528 10004.933.73924
10009.3934.7795410017.3236.1819210029.7736.2005210036.2934.9632110042.21 33.1261
10053.0932.7279410063.3335.7651910069.6737.4567610079.8739.8594710102.1246.52572
10105.2747.2101810117.9749.1702110143.36 52.542410156.0653.7860710160.8154.43978
#Mann= 3 , 0 , 0
 9855.97    0.04       0 9855.97    0.04       010160.81    0.04       0
#XS Ineff= 2 , 0
       0                               0
Bank Sta=9855.97,10160.81
Exp/Cntr=0.3,0.1

Type RM Length L Ch R = 1 ,3073.305,142.120700,142.120700,142.120700
XS GIS Cut Line= 6
871230.200106861742176.873917876871149.064781851742225.943848331
871068.705566654742260.825138796871037.046294083742277.058569272
870999.425708774742301.150944186870955.523433115742335.329952322
#Sta/Elev= 30
9840.76649.95704 9846.95 48.85699855.78348.174959870.73347.619839874.26346.96215
9891.345 45.59339913.29542.893039917.34842.335979928.81939.539389933.70238.64837
9940.12837.761739951.19935.901099973.34132.375669980.03931.455279984.38130.68264
9995.12129.6361710016.5430.1487810027.4829.3643810038.7129.1443610049.9530.20896
10054.3830.8010210061.3231.9432310085.07 38.274110096.9440.4857210103.5641.31305
10109.1741.8748610121.8544.4228810126.1144.8168210142.3946.90018 10159.2 48.8314
#Mann= 3 , 0 , 0
9840.766    0.04       09840.766    0.04       0 10159.2    0.04       0
#XS Ineff= 2 , 0
       0                               0
Bank Sta=9840.766,10159.2
Exp/Cntr=0.3,0.1

Type RM Length L Ch R = 1 ,2931.184,145.939900,145.939900,145.939900
XS GIS Cut Line= 6
871131.953339781742012.815022998871066.687525994 742081.26480478
871022.238647584742134.925057251871021.023648559742136.513697362
870990.252760695742174.682401968870911.552020894742258.864587846
#Sta/Elev= 30
9834.743 44.75549844.81944.164099865.39741.584839873.80241.166099879.21441.11896
9888.29340.565249893.03140.073829902.78439.625979917.27538.073179947.15735.97413
9960.14234.583649963.31934.108339973.12731.937319986.11228.343139994.67127.15603
9999.09426.94461 10010.627.1545410026.5327.8143410042.4627.8494410050.4628.18844
10064.1528.3532310072.3628.7135410077.8429.21973   1008730.5427510091.5331.30608
10105.2234.15699 10132.6 37.587710146.29 39.816110160.2241.2587310165.2742.00026
#Mann= 3 , 0 , 0
9834.743    0.04       09834.743    0.04       010165.27    0.04       0
#XS Ineff= 2 , 0
       0                               0
Bank Sta=9834.743,10165.27
Exp/Cntr=0.3,0.1

Type RM Length L Ch R = 1 ,2785.244,144.190700,144.190700,144.190700
XS GIS Cut Line= 6
871012.305571656741932.710331895 870953.65402609742003.563586202
870890.896596392742070.541687331870869.419862339742095.681296991
870836.806181167742140.566222549870804.102249335742193.642789355
#Sta/Elev= 30
9832.63137.993469875.45234.551559891.13533.369989900.51232.142799906.81731.46558
9913.49330.932099922.499 29.6178 9939.9826.707419952.53224.91313  9967.524.05686
9980.298   24.339982.46824.275389996.849 24.457310010.6924.3276510025.5324.88427
10035.4725.0789110040.9324.8689510049.5224.3142910061.0424.41482 10073.4 24.8772
10085.7626.3834410091.0627.2879910098.1228.3497710110.2129.6132110121.9531.33018
 10127.5 32.3304 10133.733.1763710145.4434.1975810157.19 35.542310167.3436.46956
#Mann= 3 , 0 , 0
9832.631    0.04       09832.631    0.04       010167.34    0.04       0
#XS Ineff= 2 , 0
       0                               0
Bank Sta=9832.631,10167.34
Exp/Cntr=0.3,0.1

Type RM Length L Ch R = 1 ,2641.054,145.702200,145.702200,145.702200
XS GIS Cut Line= 6
  870839.2593342741801.599942612870822.375886193741857.143910742
870806.475585552741941.375878963870802.550952905742000.677164061
870790.136281246742106.633908229870785.592413434742191.273677773
#Sta/Elev= 30
9836.90639.498919861.363 37.58399871.81537.257429882.26635.846429885.93635.57435
9903.01334.839529913.26533.633489923.51732.161289944.02130.186069954.11928.78615
9964.216 26.26849974.31324.542599984.38323.070479994.40522.1995110003.1622.17448
 10024.523.5662210034.5223.9048810054.7622.98418 10064.922.9804310074.9522.67105
10095.0522.3932110115.1522.77282 10125.223.3656610135.2523.72397 10145.324.53147
10155.3225.7384210185.3729.6977910195.3831.2093710215.4133.6550910231.7135.15929
#Mann= 3 , 0 , 0
9836.906    0.04       09836.906    0.04       010231.71    0.04       0
#XS Ineff= 2 , 0
       0                               0
Bank Sta=9836.906,10231.71
Exp/Cntr=0.3,0.1

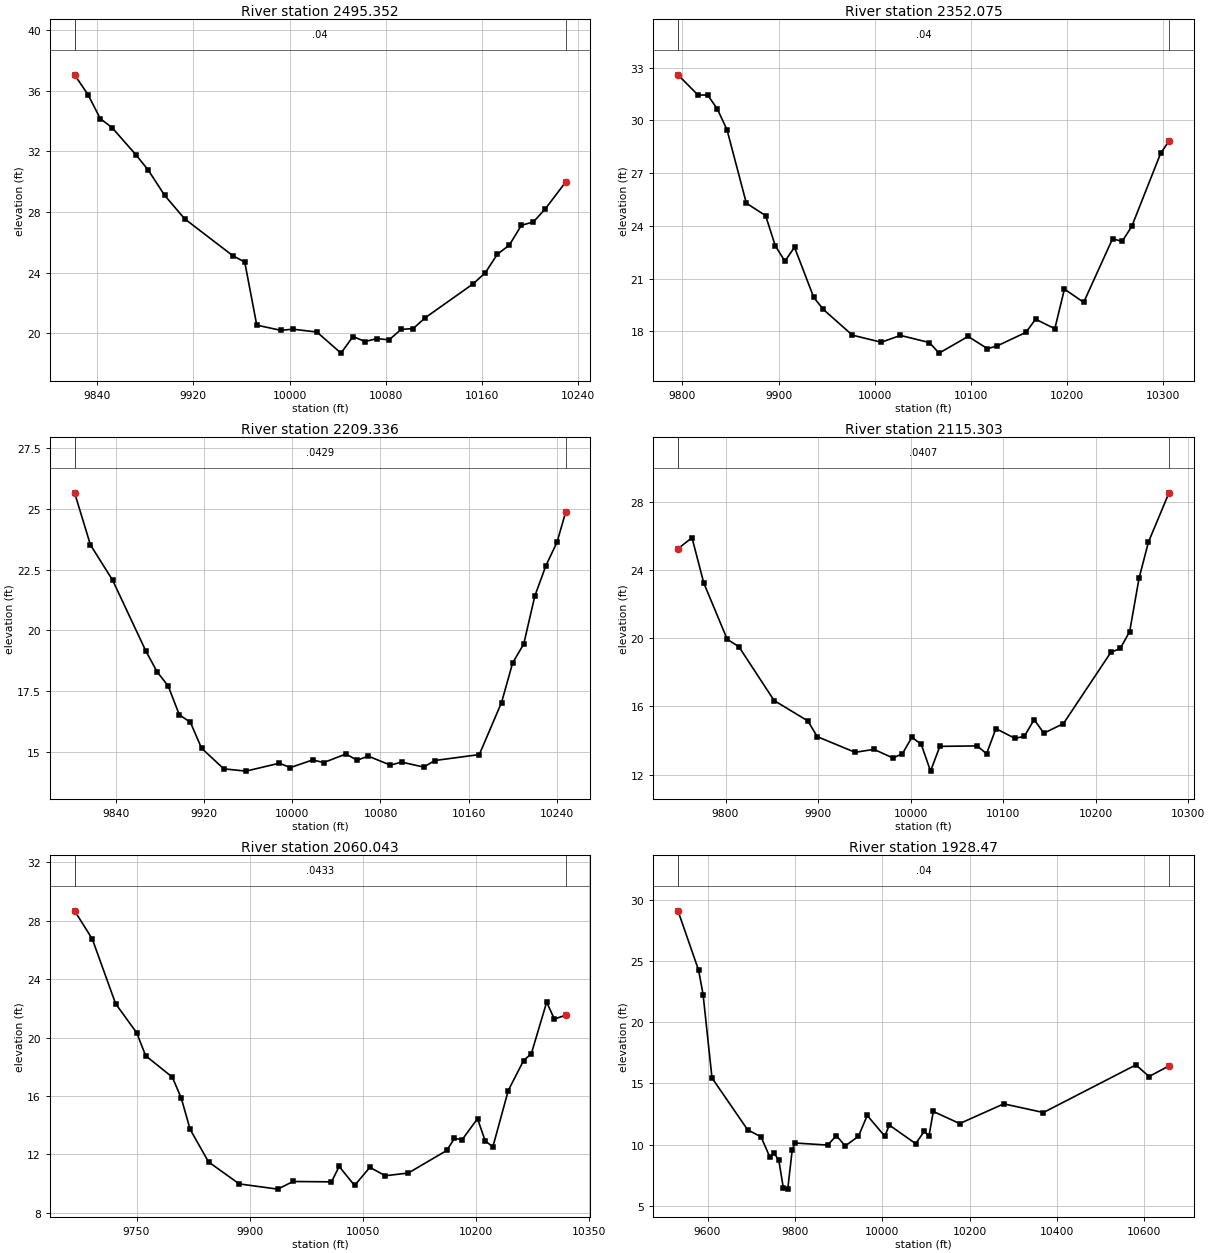
Type RM Length L Ch R = 1 ,2495.352,143.276300,143.276300,143.276300
XS GIS Cut Line= 6
870671.058965484741803.782369209870664.710416383741881.936833675
870663.043774769741979.478052718870660.334230147742058.395703953
870661.640363628742105.932042977870661.283396833742211.777480118
#Sta/Elev= 30
9821.28137.037719832.53535.719069842.56834.160019852.60133.545559872.66731.73525
  9882.730.739789896.11629.102599912.75827.553279952.76425.124759962.76524.70465
9972.76620.545759992.76920.2033310002.7720.2787810022.78 20.0919 10042.8 18.7018
 10052.819.7933810062.8119.4678210072.8119.6579410082.8219.5772910092.8220.26796
10102.8320.3164510112.8321.0317410152.8323.2740310162.8324.0016810172.8325.21395
10182.8325.8236610192.8327.1242610202.8327.3463610212.83 28.220210229.6129.97198
#Mann= 3 , 0 , 0
9821.281    0.04       09821.281    0.04       010229.61    0.04       0
#XS Ineff= 2 , 0
       0                               0
Bank Sta=9821.281,10229.61
Exp/Cntr=0.3,0.1

Type RM Length L Ch R = 1 ,2352.075,142.738800,142.738800,142.738800
XS GIS Cut Line= 6
870535.126866218741784.279221739870527.442336086741858.706521784
870520.942664867741976.151302206870514.859962977742062.675962047
870508.987097655 742114.42726025870504.985164277742293.712348602
#Sta/Elev= 30
9795.45732.599699816.28831.448489826.341 31.45059836.395 30.65459846.44829.47075
9866.554  25.2919886.599 24.58379896.61422.872629906.62921.989529916.64522.78211
9936.67519.92583 9946.6919.240439976.73617.78175 10006.817.3760910026.8517.76394
10056.92 17.356510066.9516.7559810097.1117.7053410117.2417.0129110126.7317.15114
10157.3117.9384410167.3118.6889810187.3118.1454510197.3220.4017310217.3219.64719
10247.3323.2640810257.3323.1168210267.3323.9704110297.3428.1283610306.06 28.8328
#Mann= 3 , 0 , 0
9795.457    0.04       09795.457    0.04       010306.06    0.04       0
#XS Ineff= 2 , 0
       0                               0
Bank Sta=9795.457,10306.06
Exp/Cntr=0.3,0.1

Type RM Length L Ch R = 1 ,2209.336,94.033600,94.033600,94.033600
XS GIS Cut Line= 2
870405.717056669741770.757712221870345.431829048 742212.70279694
#Sta/Elev= 30
9802.15525.672039816.52923.529599836.71422.069579866.99219.142919877.08518.30013
9887.17717.71119 9897.2716.526049907.36316.215829917.45515.150469937.64114.29954
9957.82614.204839988.10414.530759998.19614.3512410018.3814.6660510028.4714.55824
10048.6614.9107210058.7514.6531410068.8414.8234310089.0314.4517110099.1214.57689
10119.3114.37163 10129.414.6424410169.7714.8862110189.9617.0309510200.0518.66279
10210.1419.4435510220.2321.4248510230.3322.6773710240.4223.6451410248.1924.87218
#Mann= 3 , 0 , 0
9802.155  0.0429       09802.155  0.0429       010248.19  0.0429       0
#XS Ineff= 2 , 0
       0                10172.25       0
Bank Sta=9802.155,10248.19
Exp/Cntr=0.3,0.1

Type RM Length L Ch R = 1 ,2115.303,55.259600,55.259600,55.259600
XS GIS Cut Line= 6
870392.368233307741733.021397443870310.369402674 741838.42840222
870285.630314718741954.805104205870270.457717966 742065.36822896
870249.716112396742126.340260345870231.793543144742226.843343798
#Sta/Elev= 30
9748.62625.251769763.80225.894749776.47223.245449801.81119.94097 9814.4819.50295
9852.48916.34925 9888.8915.156089899.11314.232659940.00713.311999960.454 13.4854
9980.90112.980019991.12413.2263410001.3514.1892310011.4413.7923610021.5312.20912
10031.6313.66119   1007213.68717 10082.113.2264110092.19 14.702910112.7514.12886
10122.9214.2505910133.4815.2286310144.0514.4340110165.1714.9972410216.4219.17491
10226.5819.4011710236.7420.3951710246.8923.5237210257.0525.6480410279.2428.52684
#Mann= 3 , 0 , 0
9748.626  0.0407       09748.626  0.0407       010279.24  0.0407       0
#XS Ineff= 2 , 0
       0                10085.92       0
Bank Sta=9748.626,10279.24
Exp/Cntr=0.3,0.1

Type RM Length L Ch R = 1 ,2060.043,131.573000,131.573000,131.573000
XS GIS Cut Line= 3
 870404.87526688 741696.14002513870262.967092389          741785
870169.262521983742259.666483725
#Sta/Elev= 30
9667.84528.679399691.29526.748949722.22422.321089750.28920.319059762.08818.75394
9797.48417.286589809.28315.856449821.08113.713379845.47211.481679886.2449.974849
9937.2099.6180189957.59510.1412510008.5610.1157610018.7511.1731910039.149.867779
10059.52 11.110610079.91 10.533910110.4910.7226510161.4512.2672410171.6513.09481
10181.8413.0035710202.2314.4436510212.4212.9260610222.6112.51266   1024316.37084
10263.3818.4275810273.5818.8862910293.96 22.425610304.1621.2652710319.1121.53109
#Mann= 3 , 0 , 0
9667.845  0.0433       09667.845  0.0433       010319.11  0.0433       0
#XS Ineff= 2 , 0
       09891.079        10089.41       0
Bank Sta=9667.845,10319.11
Exp/Cntr=0.3,0.1

Type RM Length L Ch R = 1 , 1928.47,233.875300,233.875300,233.875300
XS GIS Cut Line= 3
870391.349681377741667.786434538870128.654852842741721.056637085
870018.653926771742570.229166048
#Sta/Elev= 30
9532.34829.112369579.64224.248449589.84522.269139610.25215.44459 9691.8811.20191
9722.49110.631019742.8988.9608659753.102 9.266999763.3058.6997479773.5096.465669
9783.7126.3521669793.9169.564385 9800.3910.124499874.9519.9549759895.11810.72322
9915.2859.8835539945.53610.673069965.70312.3765310006.0410.6759710016.1211.59308
10076.6210.0703110096.7911.1068510106.87 10.657310116.9612.7029610177.4611.71426
10278.2913.3265110369.0512.61728 10580.816.5115410611.0515.5623410656.6616.43238
#Mann= 3 , 0 , 0
9532.348    0.04       09532.348    0.04       010656.66    0.04       0
#XS Ineff= 2 , 0
       09787.301        10112.31       0
Bank Sta=9532.348,10656.66
Exp/Cntr=0.3,0.1

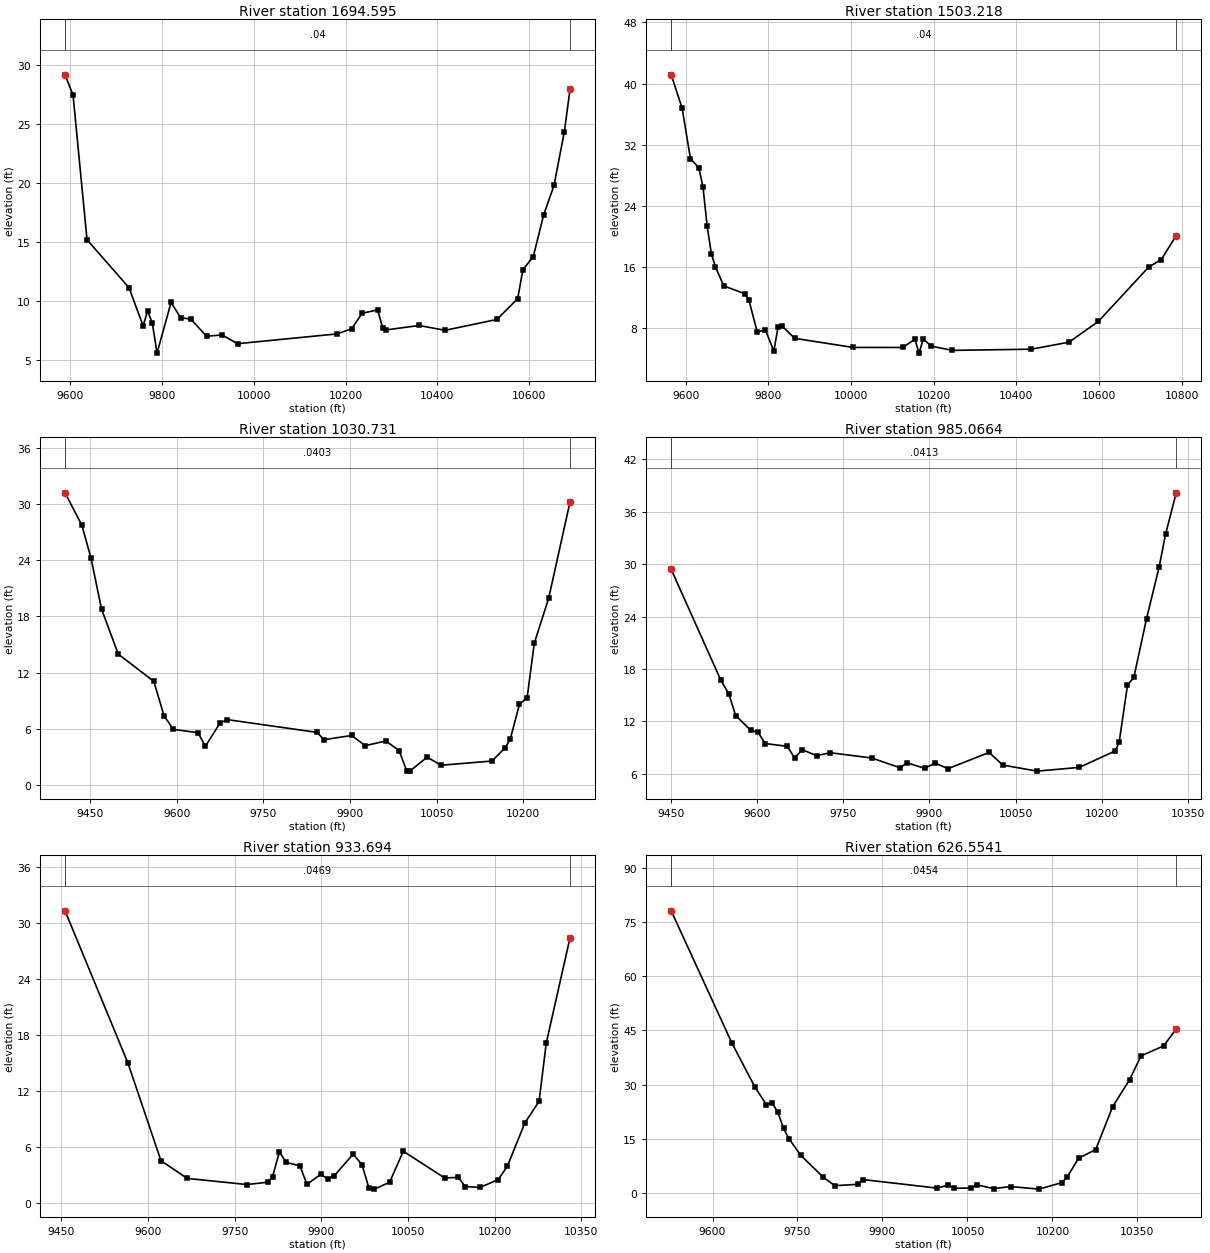
Type RM Length L Ch R = 1 ,1694.595,191.376900,191.376900,191.376900
XS GIS Cut Line= 3
870362.140740608741638.969752568870118.872931809 741684.10022374
869364.011245237742081.876572844
#Sta/Elev= 30
9588.52229.183589605.95527.468979636.46715.204879728.00211.144959758.5147.927022
9768.6859.1683469778.8568.1210369789.0265.6023489819.5389.8945019840.3188.616133
9862.9258.4744829896.8357.0369669930.7467.1396149964.6566.40217410181.087.229947
10213.337.66529910235.948.97819410269.85 9.2631110281.157.69417810288.337.569467
10360.287.94415710416.797.53537710529.838.45708410575.0410.2230210586.3512.67108
10608.9513.7751410631.5617.3030310654.17 19.813510676.7724.3764210689.19 27.9918
#Mann= 3 , 0 , 0
9588.522    0.04       09588.522    0.04       010689.19    0.04       0
#XS Ineff= 2 , 0
       09820.118        10319.31       0
Bank Sta=9588.522,10689.19
Exp/Cntr=0.3,0.1

Type RM Length L Ch R = 1 ,1503.218,472.487000,472.487000,472.487000
XS GIS Cut Line= 6
870421.198915536741624.306242291870124.280103253741584.295698214
869793.334991952741556.735932959869626.915892789741537.586014682
869419.008278263741506.468726198869209.400010677741468.585333782
#Sta/Elev= 30
9564.59541.143329591.05236.778129611.24930.156419631.44628.995169641.54526.46795
9651.64321.351439661.73117.740419671.81815.975289691.99213.507979742.42812.50005
9752.51511.700229772.6897.5178069792.8637.7400169813.0374.9692439823.1258.102547
9833.2128.2550479863.473 6.6515810004.235.46357110124.52 5.4550910154.596.519774
10164.61 4.7149810174.646.55718310194.685.62437110245.015.07380210436.595.230531
10527.596.14989310598.498.85861810720.43 15.981510750.9216.96381 10787.120.10225
#Mann= 3 , 0 , 0
9564.595    0.04       09564.595    0.04       0 10787.1    0.04       0
#XS Ineff= 2 , 0
       09766.677        10596.54       0
Bank Sta=9564.595,10787.1
Exp/Cntr=0.3,0.1

Type RM Length L Ch R = 1 ,1030.731,45.664600,45.664600,45.664600
XS GIS Cut Line= 6
870373.548354496741583.724907772870280.606278614741470.887039646
870193.471785451741360.643272866869963.518987706741005.401348998
869912.546315313740942.869620994 869845.01900242740893.410778123
#Sta/Elev= 30
9406.74531.18695 9435.9227.723889451.64924.231919469.87118.797599498.83513.99016
9560.43611.07908  9578.1 7.414869594.2275.9580949636.9145.6079579649.661 4.14726
9675.1546.652837  9687.96.9973889843.1225.6374939855.0354.8547569902.684 5.31223
9926.5084.2263459962.2454.7264279985.0823.6965089997.9821.57070110003.481.507753
10033.722.99932410057.542.13474510145.942.58444310168.754.00451710177.594.949287
10193.428.63798810206.659.32948410219.0515.1492610243.8419.91925   1028130.24179
#Mann= 3 , 0 , 0
9406.745  0.0403       09406.745  0.0403       0   10281  0.0403       0
#XS Ineff= 2 , 0
       0                               0
Bank Sta=9406.745,10281
Exp/Cntr=0.3,0.1

Type RM Length L Ch R = 1 ,985.0664,51.372400,51.372400,51.372400
XS GIS Cut Line= 6
870378.744620938741511.536264951870285.802448327741398.698263115
870198.667864823741288.454365816869968.714833664740933.212025653
869917.742108271740870.680223546 869838.18996754740833.578310553
#Sta/Elev= 30
9450.91329.397449537.11416.728619551.17615.128089563.02512.666849588.93610.98861
9601.81410.746329614.5219.457534  9652.89.1400579665.546 7.825159679.029 8.75179
9703.785 8.06941 9727.418.4073039799.5797.8046759848.9466.6876459860.8597.249998
9891.5926.6298179909.9947.2247399932.3326.58183510003.818.43892910027.636.993748
10087.196.30090310160.79 6.7282710222.998.60639610229.989.591215 10244.516.14447
10255.5317.02276 10277.623.7397910299.6729.71133 10310.7  33.41610329.25 38.1576
#Mann= 3 , 0 , 0
9450.913  0.0413       09450.913  0.0413       010329.25  0.0413       0
#XS Ineff= 2 , 0
       0                               0
Bank Sta=9450.913,10329.25
Exp/Cntr=0.3,0.1

Type RM Length L Ch R = 1 , 933.694,307.139900,307.139900,307.139900
XS GIS Cut Line= 6
870410.257858689 741468.97510591870317.315679375741356.136983357
870230.181091788 741245.89297012 870000.22808157740890.650280992
869949.255352822740828.118412312869881.727946207740778.659442649
#Sta/Elev= 30
9456.18331.309349564.97714.994119622.2314.5124059667.5512.6117619770.8281.952687
9807.6342.2028249815.4282.8120039827.3415.4570869839.2534.3166139862.8413.959149
 9874.991.9677059898.8143.0521499910.7262.5735049922.6382.9176469954.8545.218769
9970.2874.080053  9982.21.583316 9991.661.46039310017.942.19149910041.76 5.52557
10113.232.65996410137.062.71647310148.971.73524510174.341.64067910205.992.473094
10221.823.91111510252.018.53802410276.8110.89006 10289.217.1259910330.4428.44241
#Mann= 3 , 0 , 0
9456.183  0.0469       09456.183  0.0469       010330.44  0.0469       0
#XS Ineff= 2 , 0
       0                               0
Bank Sta=9456.183,10330.44
Exp/Cntr=0.3,0.1

Type RM Length L Ch R = 1 ,626.5541,0.000000,0.000000,0.000000
XS GIS Cut Line= 6
870670.943880979 740802.72709662870533.843724445740779.890950356
870439.553267588740767.818157175870362.194319281740761.162885443
870093.362216535740750.346005069869782.870648341740741.731507552
#Sta/Elev= 30
9527.07278.039139634.476 41.40989674.977 29.30039695.14124.494859705.22225.03489
9715.30422.355529725.38517.916529735.46714.96656 9755.6310.484189795.8024.388221
9815.8762.0823719855.9712.4618489865.9773.7683849996.0471.41956110016.052.219597
10026.061.379928 10056.11.43376110066.122.32826510096.181.27431910126.21 1.84868
10176.231.13248610216.252.91954710226.254.55501710246.269.69409310276.2712.04826
10306.2823.9082810336.2931.42013 10356.337.9350910396.3240.7270810418.4545.38827
#Mann= 3 , 0 , 0
9527.072  0.0454       09527.072  0.0454       010418.45  0.0454       0
#XS Ineff= 2 , 0
       0                               0
Bank Sta=9527.072,10418.45
Exp/Cntr=0.3,0.1